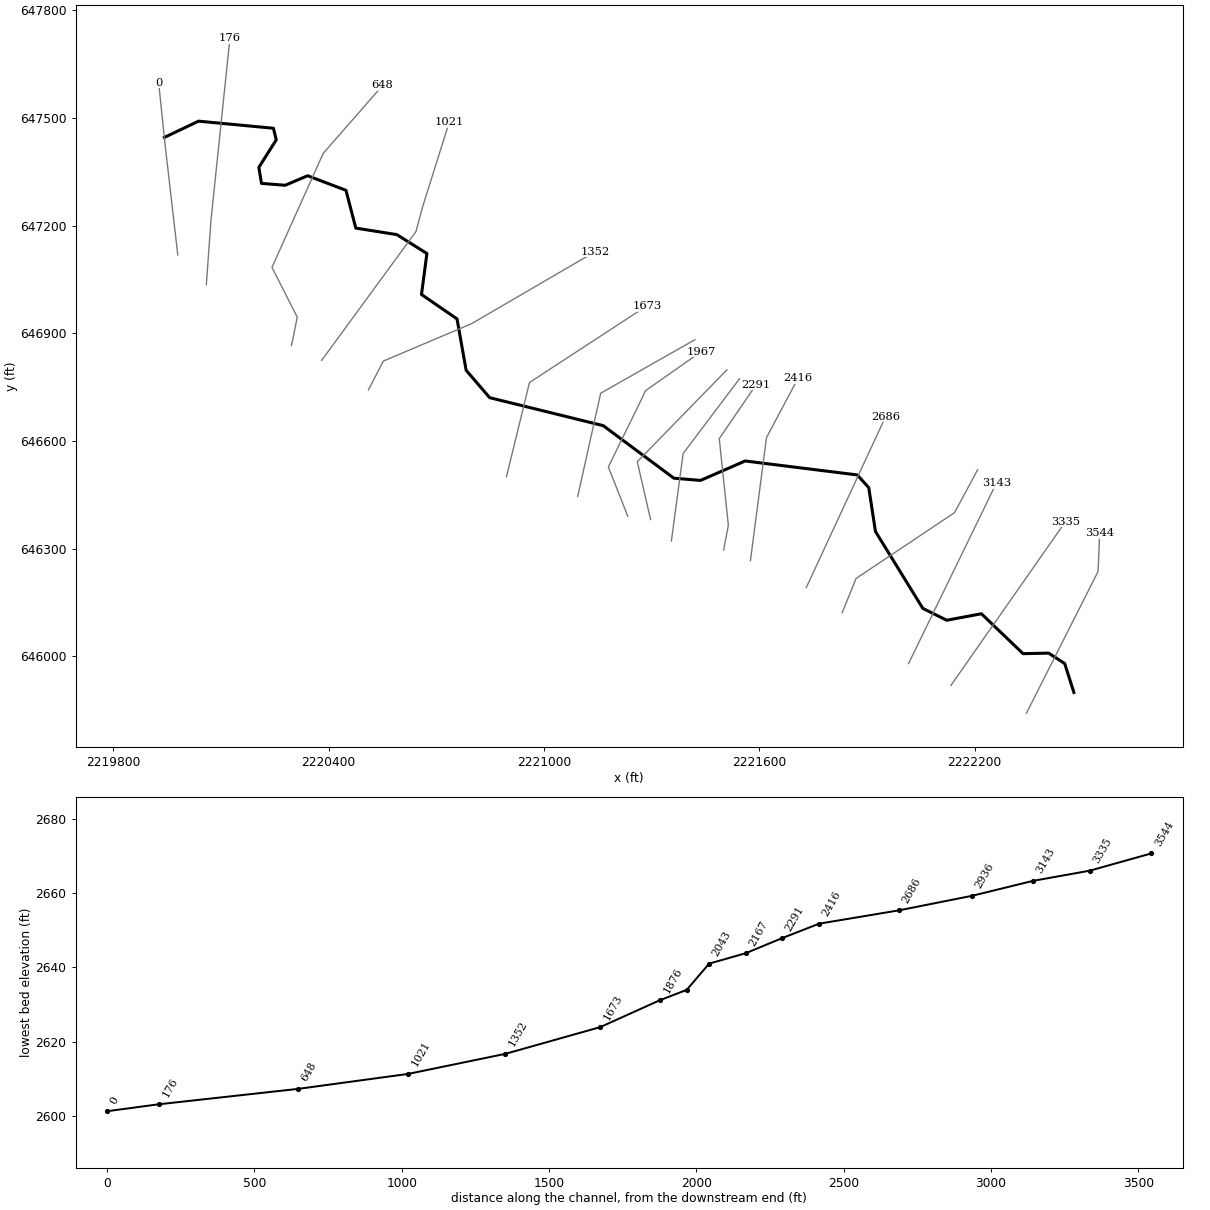
--- SUGARN2.prj (project) ---

Proj Title=SUGARN2
Current Plan=p01
Default Exp/Contr=0,0
English Units
Geom File=g01
Flow File=f01
Plan File=p01
Background Map Layer=Inundation Boundary (P100yr Value_0)
BEGIN DESCRIPTION:
----------MODEL BY WOOD PLC 2022----------
AFH study
Randolph County, WV
HEC-RAS Version: RAS 6.2
Vertical Datum: NAVD88
Projection: NAD 1983 StatePlane West Virginia S FIPS 4702 (US Feet)
Terrain: 1-meter LIDAR (FEMA Region III 3DEP collected 2016-2018)
Land Use: 2019 NLCD
Hydrologic Method:
WV SIR2010-5033 regression equations
Additional Model Notes:
Reach appears to extend into Upshur County
END DESCRIPTION:
DSS File=dss
DSS Export Rating Curves= 0
DSS Export Rating Curve Sorted= 0
DSS Export Volume Flow Curves= 0
DXF OffsetX= 0
DXF OffsetY= 0
DXF ScaleX= 0
DXF ScaleY= 0

--- SUGARN2.p01 (plan) ---

Plan Title=Floodplain
Program Version=6.20
Short Identifier=Floodplain
Geom File=g01
Flow File=f01
Subcritical Flow
K Sum by GR= 0
Std Step Tol= 0.01
Critical Tol= 0.01
Num of Std Step Trials= 20
Max Error Tol= 0.3
Flow Tol Ratio= 0.001
Split Flow NTrial= 30
Split Flow Tol= 0.02
Split Flow Ratio= 0.02
Log Output Level= 0
Friction Slope Method= 1
Unsteady Friction Slope Method= 2
Unsteady Bridges Friction Slope Method= 1
Parabolic Critical Depth
Global Vel Dist= 0 , 0 , 0
Global Log Level= 0
CheckData=True
Encroach Param=-1 ,0,0, 0
Computation Interval=0.1SEC
Output Interval=1SEC
Instantaneous Interval=Max Profile
Mapping Interval=1HOUR
Computation Time Step Use Courant=        0
Computation Time Step Use Time Series=    0
Computation Time Step Count To Double=0
Computation Time Step Max Doubling=0
Computation Time Step Max Halving=0
Computation Time Step Residence Courant=0
Run HTab= 0
Run UNet= 0
Run Sediment= 0
Run PostProcess= 0
Run WQNet= 0
Run RASMapper=-1
UNET Theta= 0
UNET Theta Warmup= 0
UNET ZTol= 0
UNET ZSATol= 0
UNET MxIter= 0
UNET Max Iter WO Improvement= 0
UNET MaxInSteps= 0
UNET DtIC= 0
UNET DtMin= 0
UNET MaxCRTS= 0
UNET WFStab= 0
UNET SFStab= 0
UNET WFX= 1
UNET SFX= 1
UNET Gravity=32.174
UNET 1D Methodology=Finite Difference
UNET DSS MLevel= 1
UNET Pardiso=0
UNET DZMax Abort= 0
UNET Use Existing IB Tables= 0
UNET Froude Reduction=False
UNET Froude Limit= 0
UNET Froude Power= 0
UNET D1 Cores= 0
UNET WindReference=Eulerian
UNET WindDragFormulation=Hsu (1988)
UNET D2 Coriolis=0
UNET D2 Cores= 0
UNET D2 Theta= 1
UNET D2 Theta Warmup= 1
UNET D2 Z Tol= 0.01
UNET D2 Volume Tol= 0.01
UNET D2 Max Iterations= 20
UNET D2 Equation= 0
UNET D2 RampUpFraction=0.1
UNET D2 TimeSlices= 1
UNET D2 Turbulence Formulation=Non-Conservative (original)
UNET D2 Eddy Viscosity=0.3
UNET D2 Transverse Eddy Viscosity=0.1
UNET D2 Smagorinsky Mixing=0
UNET D2 BCVolumeCheck=0
UNET D2 Cores=0
UNET D2 SolverType=PARDISO (Direct)
UNET D2 Minimum Iterations= 2147483647
UNET D2 Maximum Iterations= 2147483647
UNET D2 Restart Number= 10
UNET D2 Relaxation Coeff=1.3
UNET D2 SOR Precondition Iterations= 10
UNET D2 ILUT Maximum Fill= 8
UNET D2 ILUT Tolerance=1E-08
UNET D1D2 MaxIter= 0
UNET D1D2 ZTol=0.01
UNET D1D2 QTol=0.1
UNET D1D2 MinQTol=1
DSS File=dss
Write IC File= 0
Write IC File at Fixed DateTime=0
Write IC File at Sim End=0
Echo Input=False
Echo Parameters=False
Echo Output=False
Write Detailed= 0
HDF Write Warmup=0
HDF Write Time Slices=0
HDF Flush=0
HDF Compression= 1
HDF Chunk Size= 1
HDF Spatial Parts= 1
HDF Use Max Rows=0
HDF Fixed Rows= 1
Calibration Method= 0
Calibration Iterations= 20
Calibration Max Change=0.05
Calibration Tolerance=0.2
Calibration Maximum=1.5
Calibration Minimum=0.5
Calibration Optimization Method= 1
WQ AD Non Conservative
WQ ULTIMATE=-1
WQ Max Comp Step=1HOUR
WQ Output Interval=15MIN
WQ Output Selected Increments= 0
WQ Output face flow=0
WQ Output face velocity=0
WQ Output face area=0
WQ Output face dispersion=0
WQ Output cell volume=0
WQ Output cell surface area=0
WQ Output cell continuity=0
WQ Output cumulative cell continuity=0
WQ Output face conc=0
WQ Output face dconc_dx=0
WQ Output face courant=0
WQ Output face peclet=0
WQ Output face adv mass=0
WQ Output face disp mass=0
WQ Output cell mass=0
WQ Output cell source sink temp=0
WQ Output nsm pathways=0
WQ Output nsm derived pathways=0
WQ Create Restart=0
WQ Fixed Restart=0
WQ System Summary=0
WQ Write To DSS=0
Sorting and Armoring Iterations= 10
XS Update Threshold= 0.02
Bed Roughness Predictor= 0
Hydraulics Update Threshold= 0.02
Energy Slope Method= 1
Volume Change Method= 1
Sediment Retention Method= 0
Sediment TS Multiplier= 1
Warm Up Method= 0
XS Weighting Method= 0
Number of US Weighted Cross Sections= 1
Number of DS Weighted Cross Sections= 1
Upstream XS Weight=0
Main XS Weight=1
Downstream XS Weight=0
Number of DS XS's Weighted with US Boundary= 1
Upstream Boundary Weight= 1
Weight of XSs Associated with US Boundary= 0
Number of US XS's Weighted with DS Boundary= 1
Downstream Boundary Weight= 0.5
Weight of XSs Associated with DS Boundary= 0.5
Percentile Method= 0
Sediment Output Level= 3
Mass or Volume Output= 0
Output Increment Type= 1
Profile and TS Output Increment= 1
Transport Output Increment 1
XS Output Flag= 0
XS Output Increment= 10
Read HDF5 Sediment Hotstart= 0
Sediment Hotstart Type= 0
Write Gradation File= 0
Read Gradation Hotstart= 0
Write HDF5 File= 1
Write Binary Output= 1
Write DSS Sediment File= 0
DSS Sediment Output Type= 1
SV Curve= 0
Specific Gage Flag= 0
Subcell Erosion Methods= 0
Subcell Deposition Methods= 0
Advection Scheme= 1
Matrix Solver= 0
Implicit Weighting Factor= 1
Maximum Outer Loop Convergence Iterations= 5
Convergence Maximum Absolute= 0.001
Convergence RMSE= 0.0001
Grain Fractions Max Abs Error= 0.001
Max Subgrid Regions= 1
Max Subgrid Length Scale= 3.402823E+38
Initial Layer Thickness= 3.402823E+38
Min Layer Thickness= 3.402823E+38
Max Layer Thickness= 3.402823E+38
Number of Layers= 5

--- SUGARN2.f01 (steady flow) ---

Flow Title=Flow
Program Version=6.20
Number of Profiles= 1
Profile Names=P100yr
River Rch & RM=SUGARN2,Main            ,3544
     400
River Rch & RM=SUGARN2,Main            ,176
     464
Boundary for River Rch & Prof#=SUGARN2,Main            , 1
Up Type= 0
Dn Type= 1
Dn Known WS=2605.63
DSS Import GetInterval= 0
DSS Import GetPeak= 0
DSS Import FillOption= 0

--- SUGARN2.g01 (geometry) ---

Geom Title=Geometry
Program Version=6.20

River Reach=SUGARN2         ,Main
Reach XY= 30
     2222476.686645898.9099999962222450.96200003645979.590000004
2222406.40700001646008.6330000162222334.98600002646007.159000009
2222218.90800004646118.3550000042222122.38000001 646100.29900001
     2222055.662646133.2810000182221923.76900002      646347.522
2221905.01900004646469.744000018     2221873.074646505.160000011
     2221560.574 646544.049000012221436.26900002646489.883000016
2221361.96300001646496.1330000162221165.18900003646642.495000035
2220848.76900001646720.4380000082220783.21100003646796.781000003
2220757.79700004646939.8830000162220658.78000003647007.971000016
     2220673.855 647122.174000012220590.00100003647174.778999999
     2220475.763647192.9300000222220448.33500001647298.216000021
2220341.56400001647338.8410000062220279.06400003647312.279000014
2220212.91799998647317.4870000182220205.62600003647362.277999997
2220254.06399998647438.8410000212220246.25100005647471.133000001
2220037.56100002647490.925999999 2219942.2520026647445.530298379

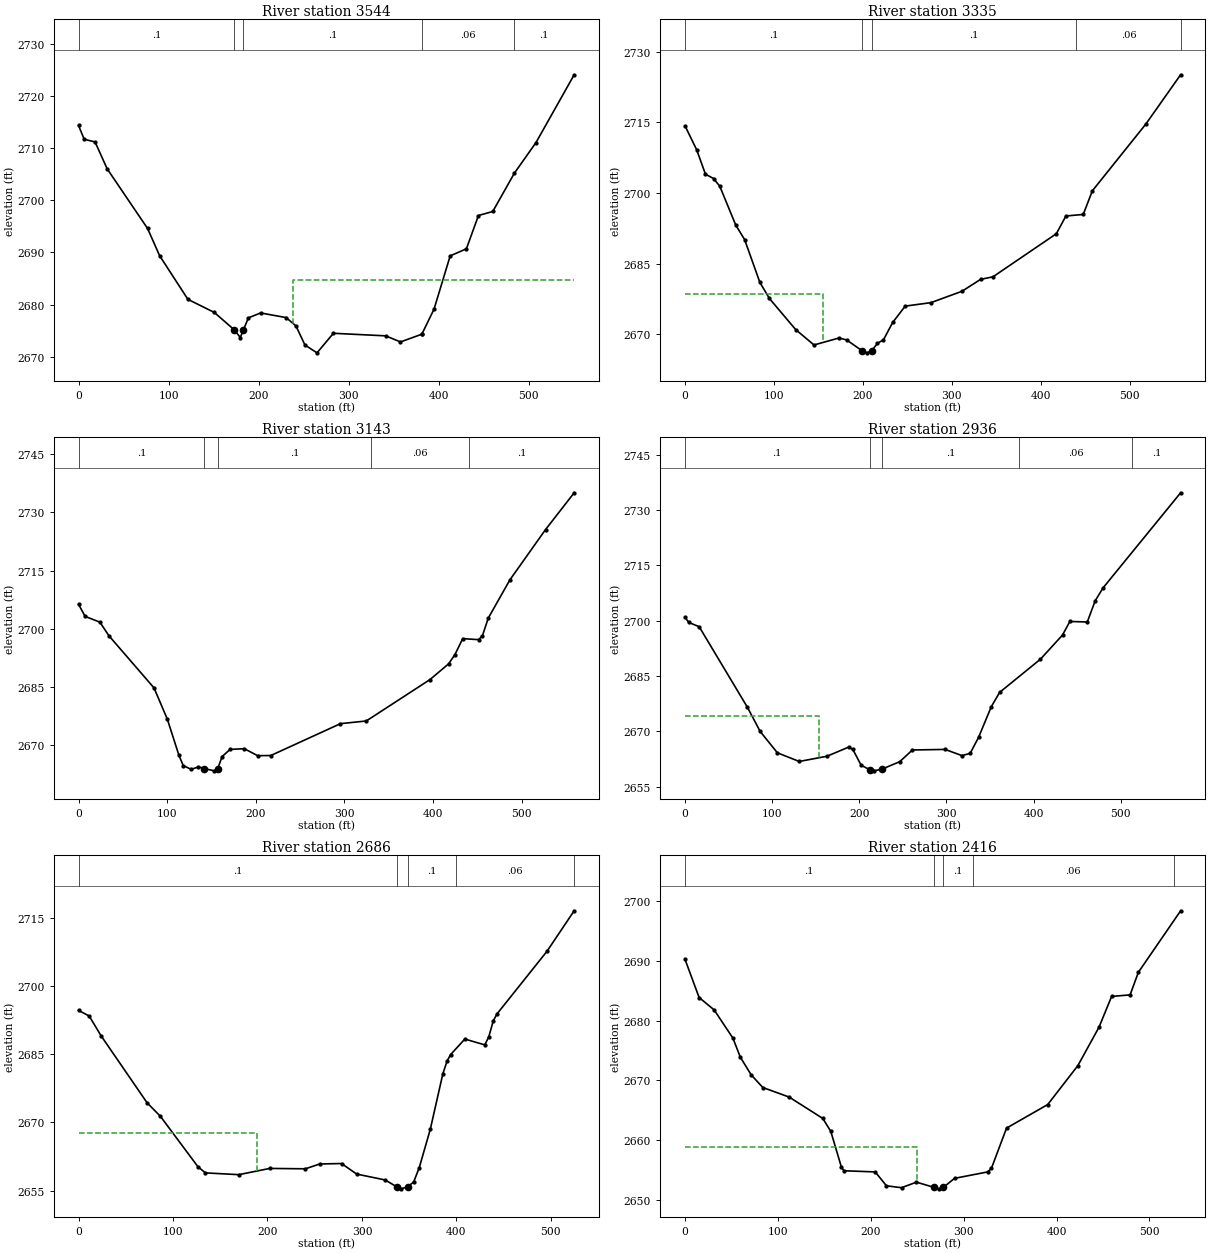
Type RM Length L Ch R = 1 ,3544    ,209.6,209.3,208.3
BEGIN DESCRIPTION:
IFA on disconnected area (is now connected with IFA)
END DESCRIPTION:
XS GIS Cut Line= 3
2222344.12699154645840.7751682242222544.02873763646236.103248163
2222548.50414985 646343.51314158
#Sta/Elev= 30
       0 2714.34     6.3  2711.7    18.4 2711.17    31.8 2706.03    76.7 2694.58
    90.1 2689.35   121.5 2680.99   150.8 2678.48   173.1 2675.13   179.7 2673.67
  183.132675.126   188.7 2677.44   202.2 2678.38   230.6 2677.49   241.5 2675.89
   251.5 2672.23   264.9 2670.73   283.1 2674.48   341.1 2673.99   357.6 2672.82
   381.4 2674.31   381.4 2674.33   394.9 2679.13   412.8 2689.33   430.8 2690.68
   444.2 2697.07   460.1 2697.84   484.1 2705.19   508.1 2711.06   550.5 2724.06
#Mann= 5 ,-1,0
       0      .1       0   173.1    .045       0  183.13      .1       0
   381.4     .06       0   484.1      .1       0
#XS Ineff= 2 , 0
                           238.7         2684.69
Permanent Ineff=
       F       F
Bank Sta=173.1,183.13
XS Rating Curve= 0 ,0
Exp/Cntr(USF)=0,0
Exp/Cntr=0.3,0.1

Type RM Length L Ch R = 1 ,3335    ,190.9,191.9,190.9
XS GIS Cut Line= 2
2222133.78261693645918.3489801372222453.02868904 646374.84102716
#Sta/Elev= 30
       0 2714.29    13.2 2709.17      23 2704.01    32.1 2703.09    39.1 2701.45
    57.1 2693.18      67 2690.13    84.2 2681.01    94.9 2677.61   124.4 2671.01
     145 2667.74   173.2 2669.23   181.8  2668.8   198.7 2666.55   204.8 2666.07
  209.872666.526   216.3 2668.08   223.1 2668.85   233.5 2672.54   247.5 2675.99
   276.4 2676.73   311.3 2679.14   332.2 2681.67   346.2 2682.22   417.4 2691.37
   428.1 2695.13   447.6 2695.46   457.8 2700.47   517.9 2714.64     557 2725.12
#Mann= 5 ,-1,0
       0      .1       0   198.7    .045       0  209.87      .1       0
     440     .06       0  557.05      .1       0
#XS Ineff= 2 , 0
          155.19 2678.65
Permanent Ineff=
       F       F
Bank Sta=198.7,209.87
XS Rating Curve= 0 ,0
Exp/Cntr(USF)=0,0
Exp/Cntr=0.3,0.1

Type RM Length L Ch R = 1 ,3143    ,210.5,206.8,202.7
XS GIS Cut Line= 2
2222015.93009499645979.5129472222222260.58596333646482.250920577
#Sta/Elev= 30
       0 2706.31     7.4 2703.18    24.1 2701.69    34.3 2698.18    85.2 2684.72
   100.2 2676.66   113.1 2667.47   118.1  2664.7   127.1 2663.72   135.3 2664.36
   142.1 2663.92   153.1 2663.34     157  2663.9     162 2667.03   170.9 2668.86
     187 2669.06     202 2667.25   216.9 2667.29   295.5 2675.51   324.6  2676.2
   396.4 2686.87   417.4 2690.92   424.5 2693.28   433.4 2697.44   451.2 2697.18
   455.6 2698.17   462.2 2702.73   486.7 2712.63   526.8 2725.57   559.1 2735.06
#Mann= 5 ,-1,0
       0      .1       0   142.1    .045       0     157      .1       0
     330     .06       0     440      .1       0
Bank Sta=142.1,157
XS Rating Curve= 0 ,0
Exp/Cntr(USF)=0,0
Exp/Cntr=0.3,0.1

Type RM Length L Ch R = 1 ,2936    ,246.1,249.7,252.3
XS GIS Cut Line= 4
2221830.94638966646121.2343343692221869.73329562646216.709795185
2222144.22524546646400.201696439 2222208.3728207646519.546022458
#Sta/Elev= 30
       0 2700.96     4.3 2699.56    16.3 2698.38    71.5  2676.6    86.3 2669.98
     106  2664.2   131.1 2661.85   162.8 2663.26   187.8 2665.74   192.6 2665.11
   202.2  2660.8   211.8 2659.66   216.7 2659.31   226.3 2659.78   226.3 2659.79
   246.5 2661.81   260.9 2664.96   298.4 2665.12   317.7 2663.45   327.2 2664.03
   336.9 2668.41   351.4 2676.67     361 2680.58   407.9 2689.59   433.2 2696.14
   441.6 2699.81   461.6 2699.67   470.7 2705.43   479.7 2708.92   568.7  2734.7
#Mann= 5 ,-1,0
       0      .1       0   211.8    .045       0   226.3      .1       0
  383.05     .06       0  513.23      .1       0
#XS Ineff= 2 , 0
          153.36 2674.14
Permanent Ineff=
       F       F
Bank Sta=211.8,226.3
XS Rating Curve= 0 ,0
Exp/Cntr(USF)=0,0
Exp/Cntr=0.3,0.1

Type RM Length L Ch R = 1 ,2686    ,267.6,270,271.3
XS GIS Cut Line= 2
2221730.99551662646191.3491259052221951.78251976646667.234625906
#Sta/Elev= 30
       0 2694.65    11.3  2693.4    24.1 2688.98    72.6  2674.3    86.6 2671.35
   126.4 2660.24   134.3 2658.88   169.6 2658.49   202.4 2659.86   240.2 2659.78
   255.3 2660.84   278.4 2660.94   294.4 2658.62   324.6 2657.32   336.6 2655.84
   341.6 2655.37   348.7 2655.85   354.8 2656.91   360.7 2660.06   372.4 2668.53
   385.6 2680.67   390.1 2683.49   393.8 2684.91   408.9 2688.33     430 2687.05
   434.2  2688.8     439 2692.34     443 2693.88   495.9 2707.66   524.6 2716.56
#Mann= 5 ,-1,0
       0      .1       0   336.6    .045       0   348.7      .1       0
     400     .06       0  524.61      .1       0
#XS Ineff= 2 , 0
          188.88 2667.74
Permanent Ineff=
       F       F
Bank Sta=336.6,348.7
XS Rating Curve= 0 ,0
Exp/Cntr(USF)=0,0
Exp/Cntr=0.3,0.1

Type RM Length L Ch R = 1 ,2416    ,124.7,125.9,127.1
XS GIS Cut Line= 3
2221575.31718399646266.0579844062221620.07130624646609.172921711
2221708.08774668646774.763174062
#Sta/Elev= 30
       0 2690.31    15.2 2683.89    31.4 2681.81    51.6 2677.08    59.6 2673.87
    71.3 2670.91    83.8 2668.79   112.1 2667.19   148.4  2663.6     157 2661.42
   168.5 2655.38   171.3 2654.82   204.8 2654.63   216.9  2652.3   233.1 2651.98
   249.2 2652.91   267.6 2652.06   273.4 2651.79   278.3 2652.06   290.2 2653.55
   325.9 2654.63   329.9 2655.23   346.2 2661.98   390.5 2665.93     423 2672.47
   445.7  2678.9   459.3 2684.07   479.2 2684.33   488.1 2688.12   533.6 2698.44
#Mann= 5 ,-1,0
       0      .1       0   267.6    .045       0   278.3      .1       0
     310     .06       0  526.02      .1       0
#XS Ineff= 2 , 0
          249.96 2658.79
Permanent Ineff=
       F       F
Bank Sta=267.6,278.3
XS Rating Curve= 0 ,0
Exp/Cntr(USF)=0,0
Exp/Cntr=0.3,0.1

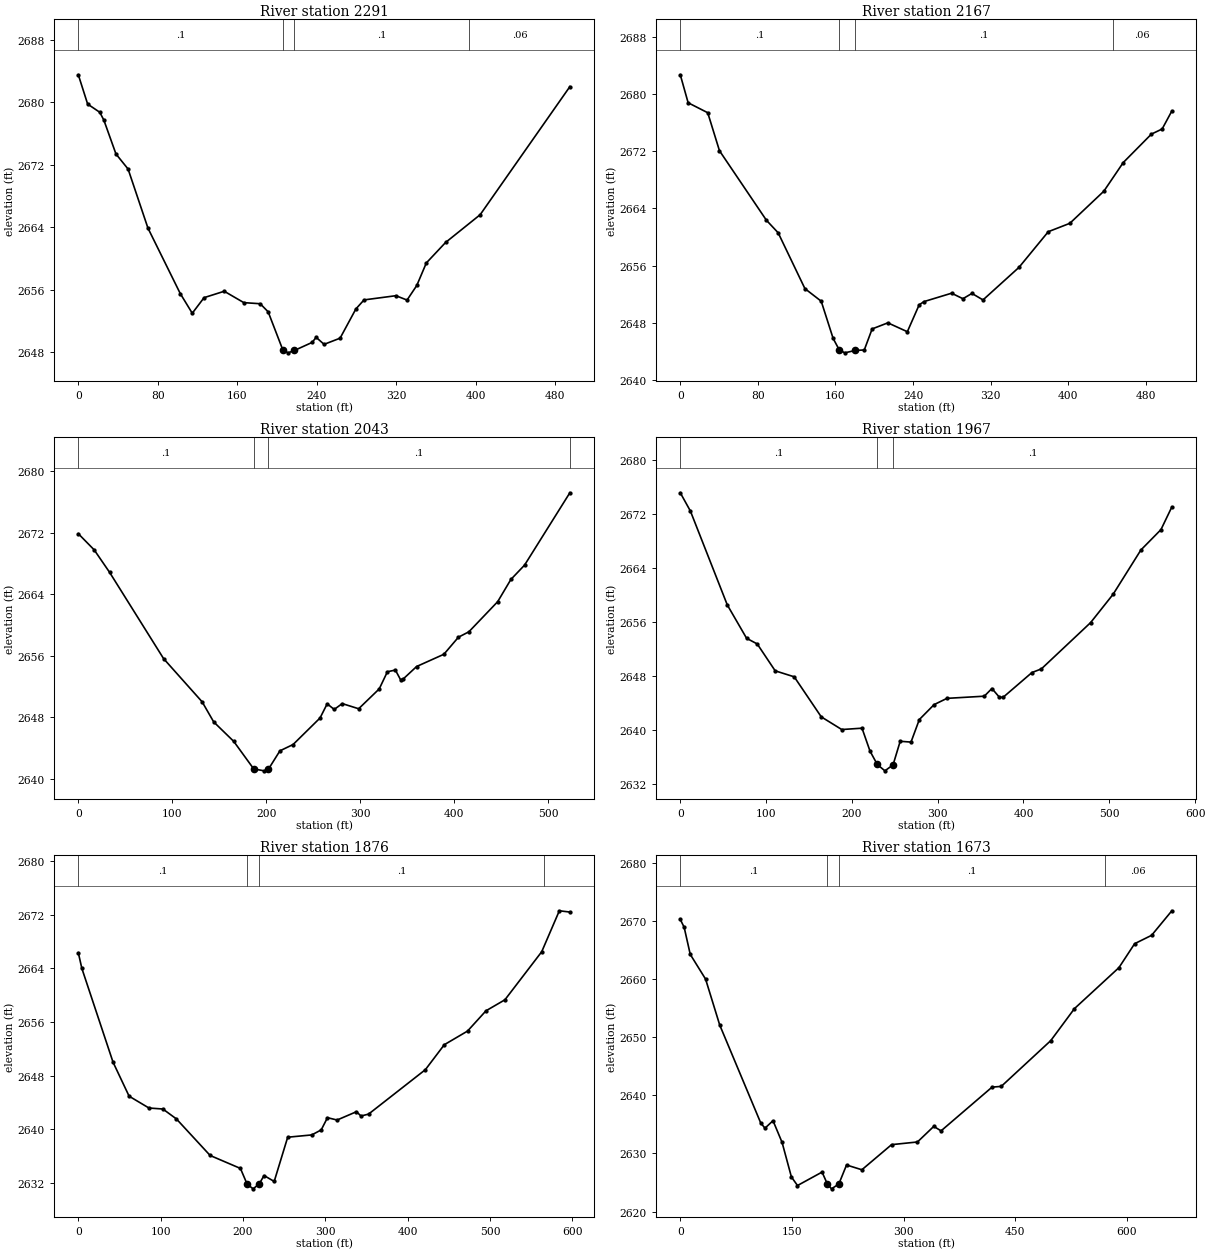
Type RM Length L Ch R = 1 ,2291    ,125.8,123.5,121.7
XS GIS Cut Line= 4
 2221500.5813164646295.9896412652221513.87329071646364.866235419
2221488.49770339646606.5384956092221591.20841398646756.375296927
#Sta/Elev= 30
       0 2683.55     9.4 2679.79    21.6 2678.74    25.7 2677.74    37.9 2673.39
    50.1 2671.46    70.1 2663.88   102.6 2655.49   114.7 2652.96   126.6 2654.96
   146.9 2655.78   166.6 2654.32   183.1 2654.18   191.1 2653.14   205.92648.241
   211.2 2647.88   217.6 2648.19   235.4 2649.22   239.4 2649.87   247.4 2648.97
   263.5 2649.76   279.4 2653.51   287.6 2654.67   319.7 2655.21   330.9 2654.65
   340.7 2656.52   350.3 2659.41   369.7 2662.04   404.5  2665.6   494.8 2682.03
#Mann= 4 ,-1,0
       0      .1       0   205.9    .045       0   217.6      .1       0
  393.15     .06       0
Bank Sta=205.9,217.6
XS Rating Curve= 0 ,0
Exp/Cntr(USF)=0,0
Exp/Cntr=0.3,0.1

Type RM Length L Ch R = 1 ,2167    ,129.3,123.6,118.8
XS GIS Cut Line= 3
2221355.06088966646321.1360804512221387.81856108646564.815114519
2221544.91100101 646773.21376002
#Sta/Elev= 30
       0 2682.66     8.1 2678.75    28.3 2677.36    40.4 2672.05    88.8 2662.34
   100.9 2660.59   128.5 2652.79   145.3 2651.03   157.6 2645.83163.86712644.242
   169.6 2643.82   180.6 2644.16   189.7 2644.22   197.8 2647.16     214 2648.01
   234.1 2646.77   246.3 2650.53   251.3 2650.98   279.7 2652.15   291.4 2651.38
   300.7 2652.12   312.1 2651.21   349.2 2655.76   379.4 2660.74   401.6 2661.91
   436.7  2666.4   456.7  2670.4   485.7 2674.37   496.8 2675.09   506.8  2677.6
#Mann= 4 ,-1,0
       0      .1       0163.8671    .045       0   180.6      .1       0
  445.87     .06       0
Bank Sta=163.8671,180.6
XS Rating Curve= 0 ,0
Exp/Cntr(USF)=0,0
Exp/Cntr=0.3,0.1

Type RM Length L Ch R = 1 ,2043    ,74,76,79.4
XS GIS Cut Line= 3
2221297.20085248646380.7255962522221260.09753872646541.982306052
2221509.83138133646798.137876044
#Sta/Elev= 30
       0 2671.85    16.9 2669.75    33.3 2666.83    90.8 2655.61   131.8    2650
   144.1 2647.39   165.5 2644.85   186.7 2641.28   197.9 2641.03   202.22641.215
   214.6 2643.63   228.6 2644.45   257.3  2647.9   264.9 2649.74   272.4 2649.01
   280.9 2649.77   298.4  2649.1   320.3 2651.68     329 2653.91   337.5 2654.13
   343.1 2652.85     346 2652.99   360.1 2654.59   389.1 2656.18   404.6  2658.4
   415.7  2659.1   446.4 2663.02   460.4  2665.9     475 2667.77   523.2 2677.17
#Mann= 4 ,-1,0
       0      .1       0   186.7    .045       0   202.2      .1       0
  523.22     .06       0
Bank Sta=186.7,202.2
XS Rating Curve= 0 ,0
Exp/Cntr(USF)=0,0
Exp/Cntr=0.3,0.1

Type RM Length L Ch R = 1 ,1967    ,89.1,91.4,92.4
XS GIS Cut Line= 5
2221233.53346889646390.2418227392221179.42915119 646527.47485113
2221273.73071532646719.8852827932221282.78764282646739.786635403
2221437.70610843646848.491045921
#Sta/Elev= 30
       0 2675.16    11.8 2672.45    54.8 2658.54    77.3  2653.6    89.7 2652.76
   110.6 2648.78   132.8 2647.89   164.3 2641.96   188.2 2640.08   211.8 2640.28
   221.1 2636.89   229.6  2634.9   238.5 2633.96     248 2634.85   256.3 2638.34
   268.9 2638.22   278.6 2641.56   295.8 2643.77   310.8  2644.7   354.3 2645.02
   363.2 2646.16     372 2644.85   376.4 2644.87   409.8 2648.52   420.9 2649.07
   478.2 2655.92   504.5 2660.13   536.8 2666.68   560.2  2669.7   572.9 2673.06
#Mann= 3 ,0,0
       0      .1       0   229.6    .045       0     248      .1       0
Bank Sta=229.6,248
XS Rating Curve= 0 ,0
Exp/Cntr(USF)=0,0
Exp/Cntr=0.3,0.1

Type RM Length L Ch R = 1 ,1876    ,202.6,202.5,202.3
XS GIS Cut Line= 3
2221093.99517649646444.9558186962221158.14275173646732.874005217
2221420.70026897646882.054412741
#Sta/Elev= 30
       0 2666.33     4.3    2664    42.2 2650.02    61.7 2644.96    85.8  2643.2
   102.7 2643.05   119.1 2641.58   160.1 2636.13   196.9  2634.2   205.1 2631.84
   212.4 2631.16   219.9 2631.94   225.6 2633.14   237.9 2632.26   254.3 2638.85
   283.5 2639.19     295 2639.94   302.6 2641.76   314.3 2641.41   337.8 2642.65
   343.3 2642.01   352.5 2642.29   421.5 2648.91   444.5 2652.63   472.7 2654.66
   495.1 2657.68   518.1 2659.32   562.8 2666.48   584.2 2672.58     597 2672.39
#Mann= 4 ,-1,0
       0      .1       0   205.1    .045       0   219.9      .1       0
  564.98     .06       0
Bank Sta=205.1,219.9
XS Rating Curve= 0 ,0
Exp/Cntr(USF)=0,0
Exp/Cntr=0.3,0.1

Type RM Length L Ch R = 1 ,1673    ,327.3,321.4,314
XS GIS Cut Line= 3
2220895.58523449 646500.152569482220959.73280972646762.710086722
 2221286.4379022646976.038069481
#Sta/Elev= 30
       0 2670.24     5.2  2668.9    13.4 2664.23      34 2659.98      53 2652.08
   108.1 2635.24   113.8 2634.34   124.6 2635.63   136.8 2631.89   149.3 2625.96
   157.5 2624.48   190.5 2626.79  197.552624.766   203.2 2623.91   213.1 2624.75
   213.1 2624.76   223.4 2628.01     244 2627.19   283.9 2631.51   318.7 2631.97
   340.6 2634.65   350.4 2633.88   418.9  2641.4   431.3 2641.53   497.8  2649.4
   529.6  2654.9   589.4 2661.95   610.5 2666.07   633.3 2667.51   660.5 2671.73
#Mann= 4 ,-1,0
       0      .1       0  197.55    .045       0   213.1      .1       0
  570.28     .06       0
Bank Sta=197.55,213.1
XS Rating Curve= 0 ,0
Exp/Cntr(USF)=0,0
Exp/Cntr=0.3,0.1

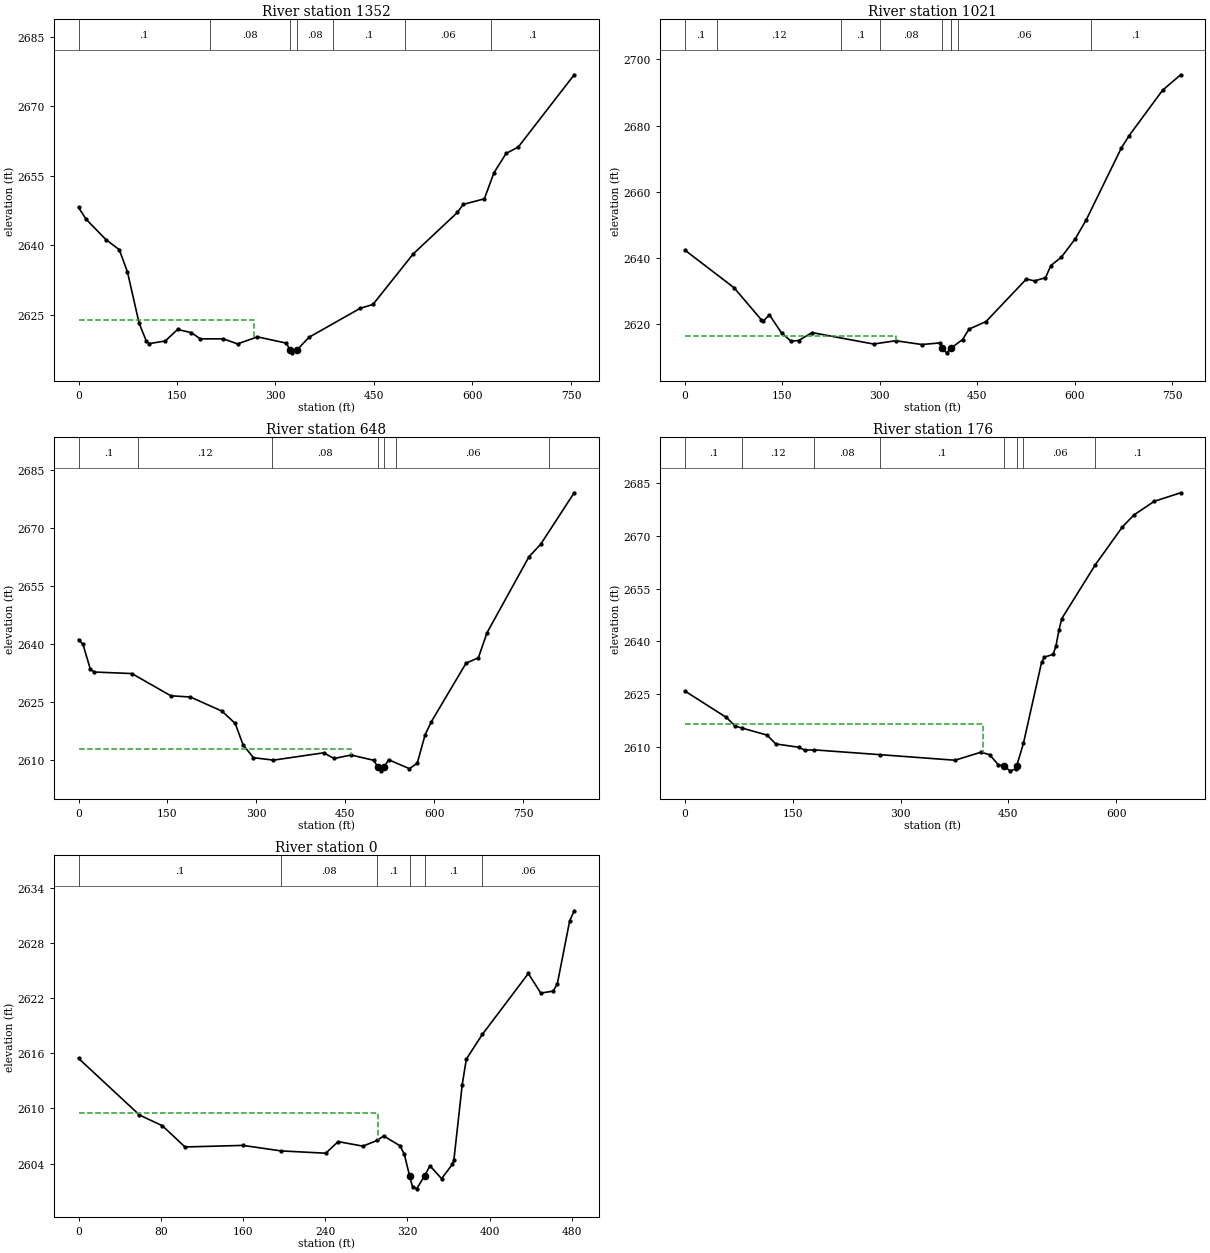
Type RM Length L Ch R = 1 ,1352    ,324,330.7,331.9
XS GIS Cut Line= 4
2220510.95040616646742.0471084762220552.47029718646822.382249731
 2220798.6179696646926.808534998 2221141.7329069 647126.71028108
#Sta/Elev= 30
       0 2648.16    11.4 2645.61    41.8 2641.19    62.1 2639.01    74.5 2634.22
    92.3 2623.12   103.1 2619.32   107.6 2618.72     132 2619.27   150.9 2621.77
   171.7 2621.09   185.7 2619.73   220.5 2619.75   242.2 2618.65   272.6 2620.17
   316.1 2618.83322.23822617.402   324.7 2616.72333.32822617.419   350.8 2620.06
   429.1 2626.35   448.4 2627.17   509.9 2638.12   577.1 2647.06   585.9  2648.8
   618.1    2650   632.7 2655.63   651.3 2659.82   669.8  2661.2   754.9 2676.81
#Mann= 7 ,-1,0
       0      .1       0  200.43     .08       0322.2382    .045       0
333.3282     .08       0  387.81      .1       0  497.81     .06       0
  627.81      .1       0
#XS Ineff= 2 , 0
          267.67 2623.77
Permanent Ineff=
       F       F
Bank Sta=322.2382,333.3282
XS Rating Curve= 0 ,0
Exp/Cntr(USF)=0,0
Exp/Cntr=0.3,0.1

Type RM Length L Ch R = 1 ,1021    ,369.2,373.4,372.9
XS GIS Cut Line= 4
2220380.54882834646824.2902671432220643.47034577647183.398835939
2220661.37199467647250.5300193252220735.96219844647487.726867288
#Sta/Elev= 30
       0 2642.32    75.5 2630.99   117.7 2621.26   120.6 2620.93     130 2622.79
   149.2 2617.17   163.5 2614.82     175 2615.02   195.7 2617.41   290.5 2613.96
   324.4 2614.96     365 2613.81   392.1  2614.3  396.382612.681   402.7  2611.3
   409.6 2612.73   427.4  2615.3   437.4 2618.47   463.5 2620.75   525.7 2633.61
   538.3 2633.04   555.1 2634.01   563.4 2637.69   579.5 2640.19   601.2 2645.85
     618 2651.55     672 2673.24   683.9 2676.94   735.4 2690.67   763.2 2695.33
#Mann= 9 ,-1,0
       0      .1       0      50     .12       0     240      .1       0
     300     .08       0  396.38    .045       0   409.6     .08       0
     410      .1       0     420     .06       0  624.55      .1       0
#XS Ineff= 2 , 0
           324.2 2616.44
Permanent Ineff=
       F       F
Bank Sta=396.38,409.6
XS Rating Curve= 0 ,0
Exp/Cntr(USF)=0,0
Exp/Cntr=0.3,0.1

Type RM Length L Ch R = 1 ,648     ,464.8,471.7,474.5
XS GIS Cut Line= 5
2220296.66020977646865.850436875 2220312.6859743646944.756394586
2220242.17504953647083.4479628982220384.88010245647401.039340837
2220550.48843547 647590.43184934
#Sta/Elev= 30
       0 2641.19     7.5 2640.01    19.7 2633.67    26.2 2632.83      90 2632.43
   155.6 2626.69   188.7 2626.36     242 2622.71   264.3 2619.52   277.5    2614
     295 2610.67   328.8 2610.04   413.4 2611.93     431 2610.47   459.8 2611.36
   498.4 2609.98504.44722608.227   509.9 2607.27515.06732608.193     523 2610.14
   558.1 2607.83   571.3 2609.26   584.5  2616.6   595.2 2620.02   653.5  2635.1
   674.4 2636.52   688.8 2642.95   759.6 2662.62   779.5 2665.89   835.9 2679.19
#Mann= 7 ,-1,0
       0      .1       0  100.52     .12       0   326.1     .08       0
504.4472    .045       0515.0673     .08       0   536.1     .06       0
  794.28      .1       0
#XS Ineff= 2 , 0
          459.34 2612.85
Permanent Ineff=
       F       F
Bank Sta=504.4472,515.0673
XS Rating Curve= 0 ,0
Exp/Cntr(USF)=0,0
Exp/Cntr=0.3,0.1

Type RM Length L Ch R = 1 ,176     ,173,176.3,177.2
XS GIS Cut Line= 3
2220059.26647357647035.1758165062220072.30504016647215.709815493
2220125.01596288 647721.68526221
#Sta/Elev= 30
       0 2625.85    57.4 2618.37    70.2 2615.86      802615.283   114.3  2613.3
   126.3 2610.79   158.4 2609.85   166.4 2609.02     1802609.098     271 2607.74
   375.8 2606.15   411.8 2608.44   423.8 2607.74   435.8 2604.91   444.5 2604.42
   452.2 2603.13     460 2603.64   461.4 2604.43     4712611.005   496.2 2634.02
   500.2 2635.53   512.3 2636.29   516.3 2638.78   520.3 2643.15   524.3 2646.49
     5712661.835   608.8 2672.64   624.9 2676.04     653  2679.9   689.7 2682.33
#Mann= 8 ,-1,0
       0      .1       0      80     .12       0     180     .08       0
     271      .1       0   444.5    .045       0   461.4      .1       0
     471     .06       0     571      .1       0
#XS Ineff= 2 , 0
        414.8592 2616.33
Permanent Ineff=
       F       F
Bank Sta=444.5,461.4
XS Rating Curve= 0 ,0
Exp/Cntr=0.3,0.1

Type RM Length L Ch R = 1 ,0       ,162.5,163.6,163.5
XS GIS Cut Line= 3
2219979.69629634647118.2841097012219945.02584386 647419.17410802
2219926.45238717 647597.47929221
#Sta/Elev= 30
       0 2615.46    59.3 2609.29    81.6 2608.12   103.6 2605.81   159.9 2605.98
   197.1 2605.38   240.5 2605.13   252.6 2606.39   276.7  2605.9   290.5 2606.52
   296.8 2607.01   312.9 2605.93     317 2604.99   322.2 2602.61     325 2601.44
     329 2601.25   336.7 2602.67   341.9 2603.76   353.2 2602.36   363.8 2603.93
   365.2 2604.41   373.3  2612.6   377.3 2615.38   392.9 2618.07   437.6  2624.7
   449.7 2622.57   461.7 2622.78   465.8 2623.56   477.8 2630.42   482.2 2631.53
#Mann= 6 ,-1,0
       0      .1       0   197.1     .08       0   290.5      .1       0
   322.2    .045       0   336.7      .1       0   392.9     .06       0
#XS Ineff= 2 , 0
        291.0197 2609.54
Permanent Ineff=
       F       F
Bank Sta=322.2,336.7
XS Rating Curve= 0 ,0
Exp/Cntr=0.3,0.1
LCMann Table=0

Chan Stop Cuts=-1
Use User Specified Reach Order=0
Composite Channel Slope=5